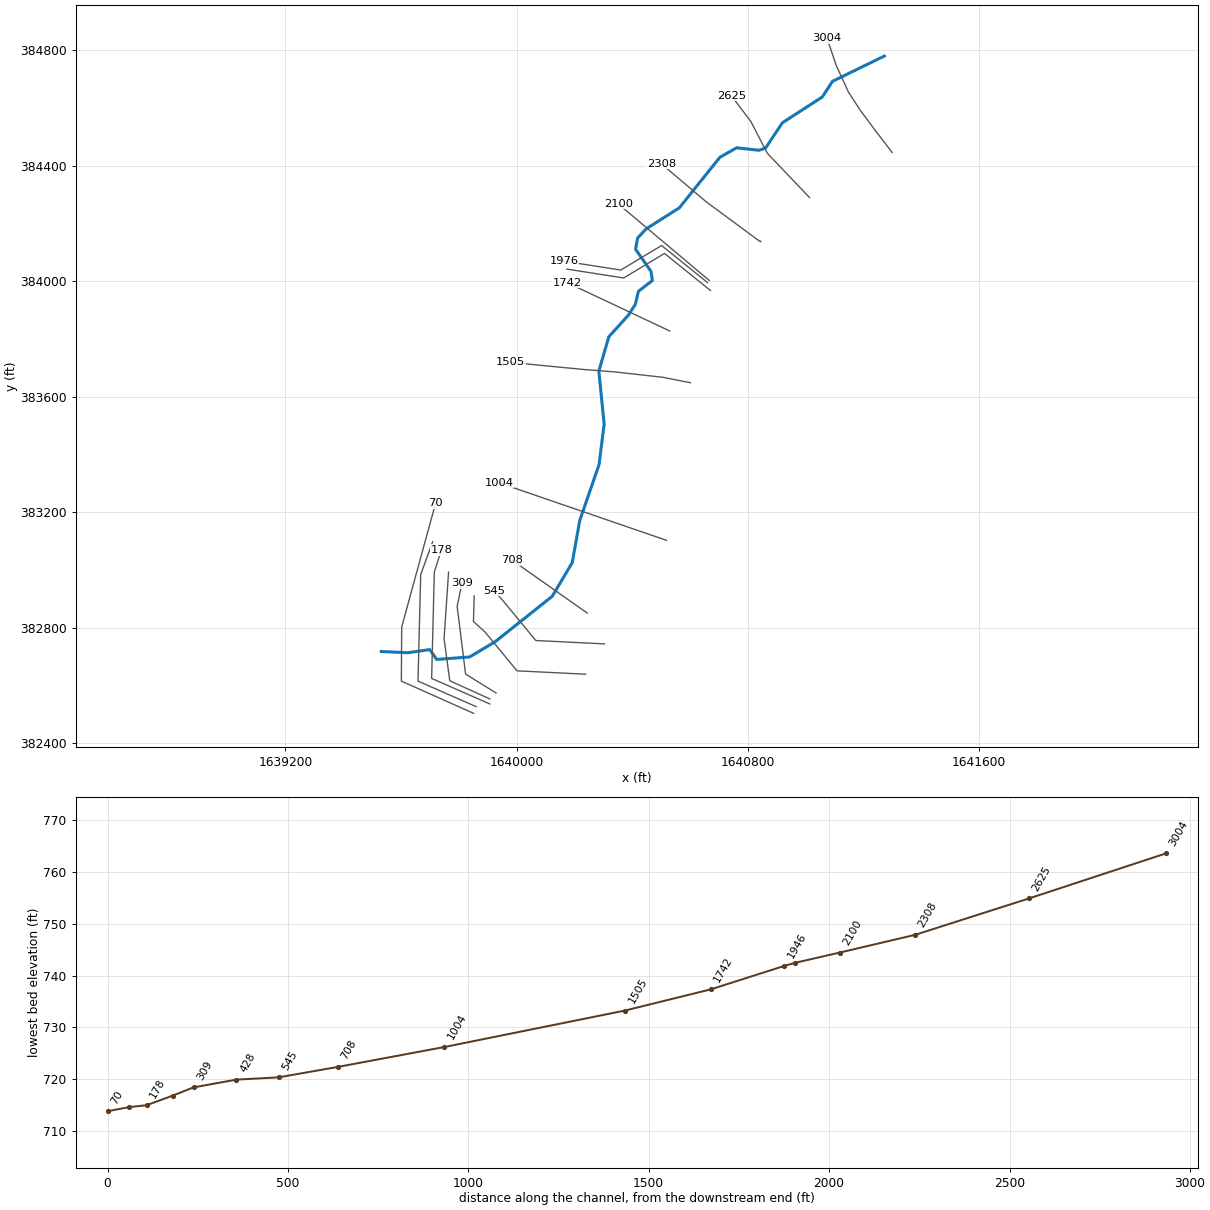
--- LOWERRN.prj (project) ---

Proj Title=LOWERRN
Current Plan=p01
Default Exp/Contr=0,0
English Units
Geom File=g01
Flow File=f01
Plan File=p01
BEGIN DESCRIPTION:
---------- MODELED AS PART OF WVEMD CTP PROGRAM, 2023----------
Stream Name: Lower Run
Flood Zone:  AFH
Wetzel County, WV
HEC-RAS Version: RAS 6.3
Vertical Datum: NAVD88
Projection: NAD 1983 StatePlane West Virginia S FIPS 4702 (US Feet)
Terrain: 1-meter West Virginia FEMA R3 South Central (collected 2018-2020)
Land Use: 2019 NLCD
Hydrologic Method:
WV SIR2010-5033 regression equations
Additional Model Notes:
None
END DESCRIPTION:
DSS File=dss
DSS Export Rating Curves= 0
DSS Export Rating Curve Sorted= 0
DSS Export Volume Flow Curves= 0
DXF OffsetX= 0
DXF OffsetY= 0
DXF ScaleX= 0
DXF ScaleY= 0

--- LOWERRN.p01 (plan) ---

Plan Title=Floodplain
Program Version=6.31
Short Identifier=Floodplain
Geom File=g01
Flow File=f01
Subcritical Flow
K Sum by GR= 0
Std Step Tol= 0.01
Critical Tol= 0.01
Num of Std Step Trials= 20
Max Error Tol= 0.3
Flow Tol Ratio= 0.001
Split Flow NTrial= 30
Split Flow Tol= 0.02
Split Flow Ratio= 0.02
Log Output Level= 0
Friction Slope Method= 1
Unsteady Friction Slope Method= 2
Unsteady Bridges Friction Slope Method= 1
Parabolic Critical Depth
Global Vel Dist= 0 , 0 , 0
Global Log Level= 0
CheckData=True
Encroach Param=-1 ,0,0, 0
Computation Interval=0.1SEC
Output Interval=1SEC
Instantaneous Interval=Max Profile
Mapping Interval=1HOUR
Computation Time Step Use Courant=        0
Computation Time Step Use Time Series=    0
Computation Time Step Count To Double=0
Computation Time Step Max Doubling=0
Computation Time Step Max Halving=0
Computation Time Step Residence Courant=0
Run HTab= 0
Run UNet= 0
Run Sediment= 0
Run PostProcess= 0
Run WQNet= 0
Run RASMapper= 0
UNET Theta= 0
UNET Theta Warmup= 0
UNET ZTol= 0
UNET ZSATol= 0
UNET MxIter= 0
UNET Max Iter WO Improvement= 0
UNET MaxInSteps= 0
UNET DtIC= 0
UNET DtMin= 0
UNET MaxCRTS= 0
UNET WFStab= 0
UNET SFStab= 0
UNET WFX= 1
UNET SFX= 1
UNET Gravity=32.17405
UNET 1D Methodology=Finite Difference
UNET DSS MLevel= 1
UNET Pardiso=0
UNET DZMax Abort= 0
UNET Use Existing IB Tables= 0
UNET Froude Reduction=False
UNET Froude Limit= 0
UNET Froude Power= 0
UNET D1 Cores= 0
UNET WindReference=Eulerian
UNET WindDragFormulation=Hsu (1988)
UNET D2 Coriolis=0
UNET D2 Cores= 0
UNET D2 Theta= 1
UNET D2 Theta Warmup= 1
UNET D2 Z Tol= 0.01
UNET D2 Volume Tol= 0.01
UNET D2 Max Iterations= 20
UNET D2 Equation= 0
UNET D2 RampUpFraction=0.1
UNET D2 TimeSlices= 1
UNET D2 Turbulence Formulation=Non-Conservative (original)
UNET D2 Eddy Viscosity=0.3
UNET D2 Transverse Eddy Viscosity=0.1
UNET D2 Smagorinsky Mixing=0
UNET D2 BCVolumeCheck=0
UNET D2 Cores=0
UNET D2 SolverType=PARDISO (Direct)
UNET D2 Minimum Iterations= 3
UNET D2 Maximum Iterations= 30
UNET D2 Restart Number= 10
UNET D2 Relaxation Coeff=1.3
UNET D2 SOR Precondition Iterations= 10
UNET D2 ILUT Maximum Fill= 8
UNET D2 ILUT Tolerance=1E-08
UNET D2 Convergence Tolerance=0.00001
UNET D1D2 MaxIter= 0
UNET D1D2 ZTol=0.01
UNET D1D2 QTol=0.1
UNET D1D2 MinQTol=1
DSS File=dss
Write IC File= 0
Write IC File at Fixed DateTime=0
Write IC File at Sim End=0
Echo Input=False
Echo Parameters=False
Echo Output=False
Write Detailed= 0
HDF Write Warmup=0
HDF Write Time Slices=0
HDF Flush=0
HDF Compression= 1
HDF Chunk Size= 1
HDF Spatial Parts= 1
HDF Use Max Rows=0
HDF Fixed Rows= 1
Calibration Method= 0
Calibration Iterations= 20
Calibration Max Change=0.05
Calibration Tolerance=0.2
Calibration Maximum=1.5
Calibration Minimum=0.5
Calibration Optimization Method= 1
WQ AD Non Conservative
WQ ULTIMATE=-1
WQ Max Comp Step=1HOUR
WQ Output Interval=15MIN
WQ Output Selected Increments= 0
WQ Create Restart=0
WQ Fixed Restart=0
WQ System Summary=0
WQ Write To DSS=0
Sorting and Armoring Iterations= 10
XS Update Threshold= 0.02
Bed Roughness Predictor= 0
Hydraulics Update Threshold= 0.02
Energy Slope Method= 1
Volume Change Method= 1
Sediment Retention Method= 0
Sediment TS Multiplier= 1
Warm Up Method= 0
XS Weighting Method= 0
Number of US Weighted Cross Sections= 1
Number of DS Weighted Cross Sections= 1
Upstream XS Weight=0
Main XS Weight=1
Downstream XS Weight=0
Number of DS XS's Weighted with US Boundary= 1
Upstream Boundary Weight= 1
Weight of XSs Associated with US Boundary= 0
Number of US XS's Weighted with DS Boundary= 1
Downstream Boundary Weight= 0.5
Weight of XSs Associated with DS Boundary= 0.5
Percentile Method= 0
Sediment Output Level= 3
Mass or Volume Output= 0
Output Increment Type= 1
Profile and TS Output Increment= 1
Transport Output Increment 1
XS Output Flag= 0
XS Output Increment= 10
Read HDF5 Sediment Hotstart= 0
Sediment Hotstart Type= 0
Write Gradation File= 0
Read Gradation Hotstart= 0
Write HDF5 File= 1
Write Binary Output= 1
Write DSS Sediment File= 0
DSS Sediment Output Type= 1
SV Curve= 0
Specific Gage Flag= 0
Subcell Erosion Methods= 0
Subcell Deposition Methods= 0
Advection Scheme= 1
Matrix Solver= 0
Implicit Weighting Factor= 1
Maximum Outer Loop Convergence Iterations= 5
Convergence Maximum Absolute= 0.001
Convergence RMSE= 0.0001
Grain Fractions Max Abs Error= 0.001
Max Subgrid Regions= 1
Max Subgrid Length Scale= 3.402823E+38
Initial Layer Thickness= 3.402823E+38
Min Layer Thickness= 3.402823E+38
Max Layer Thickness= 3.402823E+38
Number of Layers= 5

--- LOWERRN.f01 (steady flow) ---

Flow Title=Flow
Program Version=6.31
Number of Profiles= 1
Profile Names=F01pct
River Rch & RM=LOWERRN,Main,3004
     653
Boundary for River Rch & Prof#=LOWERRN,Main            , 1
Up Type= 0
Dn Type= 3
Dn Slope=0.01697
DSS Import GetInterval= 0
DSS Import GetPeak= 0
DSS Import FillOption= 0

--- LOWERRN.g01 (geometry) ---

Geom Title=Geometry
Program Version=6.30

River Reach=LOWERRN         ,Main
Reach XY= 30
     1641272.393      384779.9331641093.29401945384692.470019445
     1641057.914      384638.268     1640919.716       384548.86
     1640862.258      384462.177     1640839.472      384453.509
      1640761.21      384462.177     1640703.504      384429.237
     1640563.077      384254.137     1640448.407      384181.323
     1640418.935       384149.87     1640411.753      384110.738
     1640465.001       384034.21     1640469.954      384002.508
     1640421.659      383965.111     1640410.762       383919.54
1640386.59405439383881.843799167     1640319.373      383807.843
       1640284.7      383688.467     1640303.027      383504.203
     1640285.195      383364.024     1640218.511      383170.845
     1640192.583      383024.953     1640123.314      382908.473
     1639925.181      382750.586     1639837.337      382698.343
1639723.55275825382689.8483626261639699.94369781382723.929906565
     1639624.112      382713.049      1639531.92      382717.153

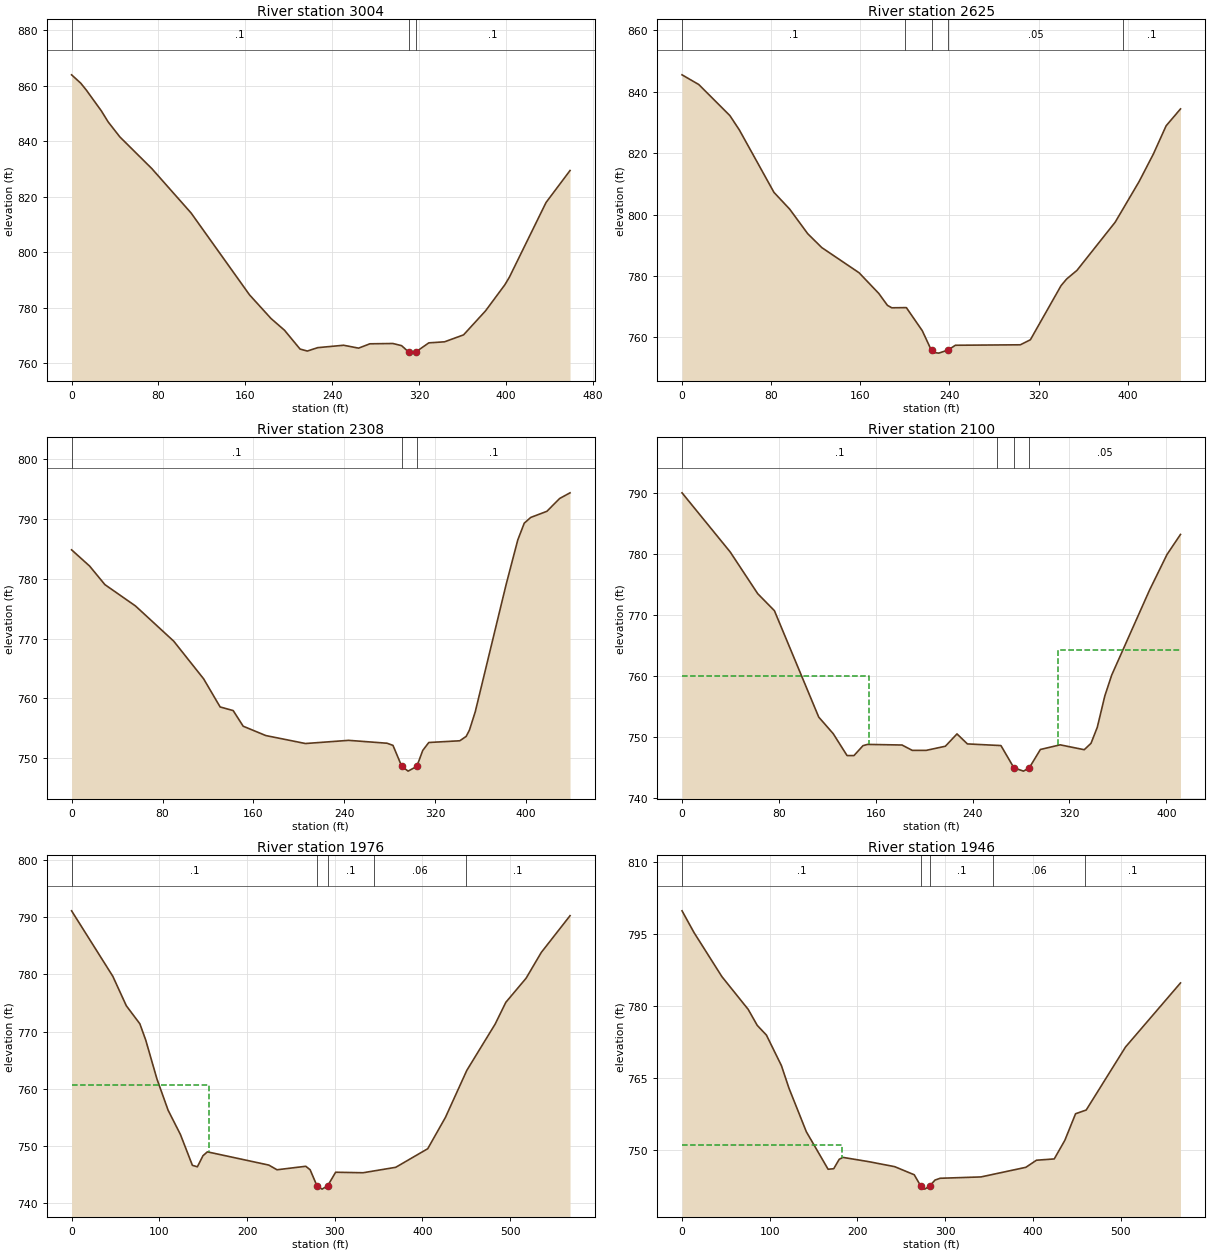
Type RM Length L Ch R = 1 ,3004    ,379,379.2,377.3
XS GIS Cut Line= 6
1641299.75138918384445.7829157561641242.18719985 384521.03834267
1641189.50128159384591.9643819181641148.41770235384655.056119248
1641106.76161768384746.0864490121641074.32287975384841.383119211
#Sta/Elev= 30
       0  863.92     8.5  860.88    13.5  858.46    27.4  850.93    33.7  846.94
    44.5  841.53      74  830.08   110.2  814.06   163.9  784.61   183.8  776.04
   196.1  771.86   210.5  765.05   217.2  764.34   226.7  765.56   250.6  766.43
   264.4  765.39   274.8  766.95     296  767.06     304  766.29  310.42764.0395
   312.8  763.59   317.2  764.04   329.1  767.29   343.6  767.67   361.1  770.17
   381.4  778.85   399.1  788.21   403.3  790.95   437.1   817.9   459.2  829.42
#Mann= 3 ,-1,0
       0      .1       0  310.42    .045       0   317.2      .1       0
Bank Sta=310.42,317.2
XS Rating Curve= 0 ,0
Exp/Cntr(USF)=0,0
Exp/Cntr=0.3,0.1

Type RM Length L Ch R = 1 ,2625    ,313.8,316.4,318.7
XS GIS Cut Line= 4
1641013.84433477384289.6612176181640867.17257574384443.821369215
1640811.02162439384552.7686198371640743.71448536384642.198234884
#Sta/Elev= 30
       0  845.46      15  842.31    42.9  832.21    51.4  827.55    82.5  807.21
    96.6  801.76   112.8  793.76   125.4  789.25   158.9  781.05   176.6  774.31
   184.3  770.46   188.2  769.66   201.3  769.72   215.6   762.2   222.6  756.73
   224.5  755.92   227.1  755.06   230.4  754.91  238.84755.9497   245.3  757.47
   303.6  757.62   312.6  759.26   340.1  776.85   345.1  779.02   354.4  781.84
   388.7  797.52   410.2  810.76     423  819.72   434.4  828.87   447.3  834.37
#Mann= 5 ,-1,0
       0      .1       0     200     .05       0   224.5    .045       0
  238.84     .05       0  395.35      .1       0
Bank Sta=224.5,238.84
XS Rating Curve= 0 ,0
Exp/Cntr(USF)=0,0
Exp/Cntr=0.3,0.1

Type RM Length L Ch R = 1 ,2308    ,208,208.4,207.9
XS GIS Cut Line= 4
1640845.40827851384138.3420932171640843.45030588384136.640619454
1640656.57015583384274.890398333 1640501.2691976384406.429461309
#Sta/Elev= 30
       0  784.83    15.9  782.11    29.3  779.02    56.2  775.46    89.9  769.57
   116.2  763.28   130.7  758.59   142.2  757.98     151  755.37   170.9  753.81
   205.8  752.48   243.8  753.01   277.6  752.53   282.8  752.17   290.5  748.68
   296.1  747.87   303.8  748.67     309  751.33   314.3  752.65   341.6  752.94
   347.2  753.67   350.1  754.73   355.2  757.79   382.4  779.07   392.6  786.47
   398.3  789.28     404  790.24   418.2  791.26   429.5  793.41   438.6  794.35
#Mann= 3 ,-1,0
       0      .1       0   290.5    .045       0   303.8      .1       0
Bank Sta=290.5,303.8
XS Rating Curve= 0 ,0
Exp/Cntr(USF)=0,0
Exp/Cntr=0.3,0.1

Type RM Length L Ch R = 1 ,2100    ,114.3,124,129.4
XS GIS Cut Line= 2
1640666.49387386384002.8677429091640351.60549178384268.036906764
#Sta/Elev= 30
       0  790.08    39.8  780.38    62.5  773.55    76.3  770.76   112.9  753.32
   124.9  750.59   136.3  747.01     142  747.01   149.5  748.64   153.3  748.84
   181.7  748.74   190.2  747.86   201.6  747.86   217.5  748.54   227.1  750.56
   235.7  748.92   263.4  748.65   274.1745.0063     282  744.46   286.8     745
     296  748.01   312.3  748.77   332.2  747.97   337.8  749.02     343  751.66
   349.2  756.79   354.9  760.21   386.1  774.12   400.5  779.95   411.7  783.26
#Mann= 4 ,-1,0
       0      .1       0     260     .05       0   274.1    .045       0
   286.8     .05       0
#XS Ineff= 2 , 0
          154.57     760  310.23          764.26
Permanent Ineff=
       F       F
Bank Sta=274.1,286.8
XS Rating Curve= 0 ,0
Exp/Cntr(USF)=0,0
Exp/Cntr=0.3,0.1

Type RM Length L Ch R = 1 ,1976    ,28.9,29.4,29.1
XS GIS Cut Line= 4
1640660.66009115383995.4135648391640501.79484864384123.727799175
 1640360.4684971384038.6736713471640163.83834828384069.519898836
#Sta/Elev= 30
       0  791.08      47  779.65    62.4   774.5    77.8  771.36    84.5  768.52
    97.3  761.72     110  756.27   124.1  752.01   137.7  746.64   143.4  746.38
   149.8  748.32   154.8  748.99   224.8  746.68   234.2  745.86   266.9  746.47
   271.9  745.87  279.65743.0807   285.5  742.48   291.9743.0626     301  745.43
   332.2  745.34   369.5  746.29     406  749.54   426.2  755.02   450.5  763.21
   482.9  771.32     495   775.1   518.1  779.31   535.4  783.81   568.2  790.23
#Mann= 5 ,-1,0
       0      .1       0  279.65    .045       0   291.9      .1       0
  344.21     .06       0  449.16      .1       0
#XS Ineff= 2 , 0
           157.1  760.74
Permanent Ineff=
       F       F
Bank Sta=279.65,291.9
XS Rating Curve= 0 ,0
Exp/Cntr(USF)=0,0
Exp/Cntr=0.3,0.1

Type RM Length L Ch R = 1 ,1946    ,208.7,204.6,198
XS GIS Cut Line= 4
1640670.77309883383967.9176574821640511.90785632384096.231891817
1640370.58150477 384011.177763991640173.95135595384042.023991479
#Sta/Elev= 30
       0  799.85    13.7  795.31    45.5  786.13    75.4  779.33    85.7     776
    96.2  773.97   113.3  767.61   121.9  762.91   141.7  753.84   166.5  746.03
   172.9  746.14   179.2  748.11   183.4   748.5   212.6  747.62   242.4  746.57
   264.7  744.88  271.89742.6049   276.7  741.89   282.5  742.58   288.4  743.78
   294.2  744.15   340.8  744.43   391.9  746.43     404  747.91   424.3  748.18
   436.4  752.07   448.6  757.59   460.7  758.36   505.5  771.48   568.2  784.83
#Mann= 5 ,-1,0
       0      .1       0  271.89    .045       0   282.5      .1       0
  354.21     .06       0  459.16      .1       0
#XS Ineff= 2 , 0
          182.46  751.18
Permanent Ineff=
       F       F
Bank Sta=271.89,282.5
XS Rating Curve= 0 ,0
Exp/Cntr(USF)=0,0
Exp/Cntr=0.3,0.1

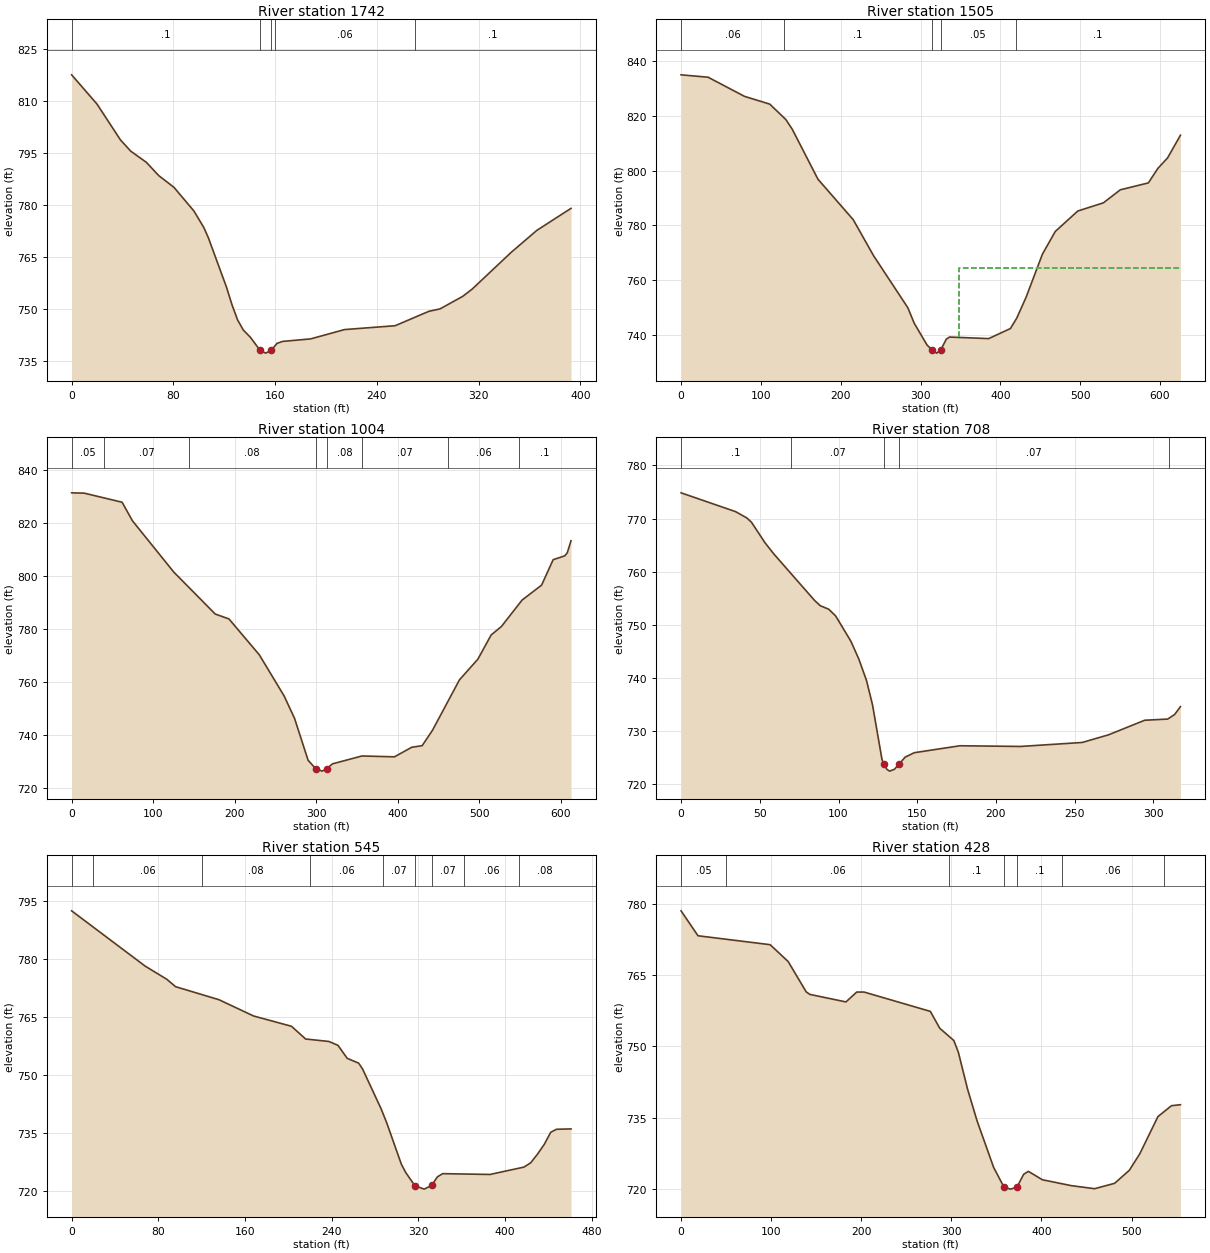
Type RM Length L Ch R = 1 ,1742    ,235.2,237.1,238.9
XS GIS Cut Line= 2
 1640530.1708262383827.4752177061640174.99964062383995.107635676
#Sta/Elev= 30
       0  817.47      20  809.03    38.4  798.73    46.5  795.49    58.7   792.3
    68.5  788.46    80.5  785.07    96.2  778.25     104  773.48   107.5  770.58
   121.7  756.43   126.1  751.28   130.5  746.92     135     744   140.6   741.9
   148.2  738.15   152.6  737.35   157.1  738.22   161.5  740.16   165.9  740.72
     188  741.45   214.6  744.13   254.4  745.24   280.9  749.38   289.8   750.1
   307.5  753.69   314.9  755.76   345.5  766.31   365.9  772.71   392.7  779.03
#Mann= 5 ,-1,0
       0      .1       0   148.2    .045       0   157.1      .1       0
     160     .06       0     270      .1       0
Bank Sta=148.2,157.1
XS Rating Curve= 0 ,0
Exp/Cntr(USF)=0,0
Exp/Cntr=0.3,0.1

Type RM Length L Ch R = 1 ,1505    ,502.4,501,499
XS GIS Cut Line= 6
1640601.29051575 383648.451177091640504.66078776383667.394708753
1640414.34732009383677.4855678381640336.37175426383686.158778846
1640235.03698318383693.9999705111639980.09195501383718.676102251
#Sta/Elev= 30
       0  835.06    33.8  834.19    79.5  827.18   111.1  824.35   131.2  818.73
   139.3  815.16   171.5  796.88   215.7  782.07   241.2  768.89   284.1  749.87
   292.1   744.2   308.2  736.22  314.81734.3609   320.2  733.27  325.15734.3652
   332.3  738.39   336.3  739.15   385.4  738.58   412.6  742.26   420.6  746.11
   432.2  753.69   452.7  769.47   468.8  777.77     497  785.25   529.1  788.24
   550.3  793.01   585.4  795.53   597.4  800.86   609.5  804.68   625.6  812.97
#Mann= 5 ,-1,0
       0     .06       0  128.47      .1       0  314.81    .045       0
  325.15     .05       0  419.44      .1       0
#XS Ineff= 2 , 0
                          348.07          764.26
Permanent Ineff=
       F       F
Bank Sta=314.81,325.15
XS Rating Curve= 0 ,0
Exp/Cntr(USF)=0,0
Exp/Cntr=0.3,0.1

Type RM Length L Ch R = 1 ,1004    ,296.3,295.4,293.6
XS GIS Cut Line= 6
1640518.63812201383102.5408515931640429.98213135383133.023402169
1640347.23459342383161.4685552571640276.30822609383185.849740088
1640110.81315026383242.7384058391639939.40732509383301.658563584
#Sta/Elev= 30
       0  831.47    15.4  831.35    61.9  827.91    74.6  820.89   125.3   801.5
   176.1  785.64     193  783.77   230.2  770.21   260.7  754.62   273.4  746.19
     290  730.37   299.4  727.14   307.2  726.23  312.79727.1497   319.9  728.98
   356.1  731.96     396  731.64   417.2  735.26   429.9  735.85   442.6  741.68
   475.7  760.76   498.3  768.58   514.5   777.7   527.2  780.95   552.5  790.92
   576.4  796.56   590.6  806.19   604.8  807.63   607.9  808.81   612.5  813.33
#Mann= 8 ,-1,0
       0     .05       0      40     .07       0  143.75     .08       0
   299.4    .045       0  312.79     .08       0  356.25     .07       0
  461.25     .06       0  548.75      .1       0
Bank Sta=299.4,312.79
XS Rating Curve= 0 ,0
Exp/Cntr(USF)=0,0
Exp/Cntr=0.3,0.1

Type RM Length L Ch R = 1 ,708     ,164.8,163.7,162.1
XS GIS Cut Line= 2
1640244.42014569382850.5539503721639985.08224817383033.164659277
#Sta/Elev= 30
       0  774.84    34.6   771.3    41.8   770.1    44.7  769.31    53.3  765.44
      59  763.29    84.9  754.53    88.4  753.57    93.8   752.9    98.2  751.64
   107.9  746.85   112.9  743.52   117.8  739.47   121.6   734.9   127.6  724.64
   128.6723.7909   130.8  722.71   132.5  722.39   135.5  722.73   138.7 723.767
   142.3  725.02   148.1  725.86   177.1  727.17   215.6  727.04   254.8  727.79
   271.5  729.23   294.5  731.98   309.1   732.2   313.5  733.06   317.2  734.55
#Mann= 5 ,-1,0
       0      .1       0      70     .07       0   128.6    .045       0
   138.7     .07       0     310     .06       0
Bank Sta=128.6,138.7
XS Rating Curve= 0 ,0
Exp/Cntr(USF)=0,0
Exp/Cntr=0.3,0.1

Type RM Length L Ch R = 1 ,545     ,117,117,117
XS GIS Cut Line= 5
1640303.90223613382743.653693562 1640066.6647345382755.310862753
1640018.97716584382813.1975579891639955.39395967382890.380146417
1639924.04096557382927.318118917
#Sta/Elev= 30
       0  792.49    67.9  778.16    87.9  774.75    95.9  772.84     136  769.46
     168  765.24     203  762.57     216  759.28   237.5  758.64   245.9  757.63
   254.4  754.27     265  753.02   268.6   751.5   285.8  741.13   290.9  737.54
   304.4  726.82   308.4  724.69   316.9  721.25   325.5  720.38   332.4  721.35
   337.6  723.55   342.5  724.39   386.2  724.18   417.6  726.09   423.8  727.21
     430  729.42   436.3  731.98   442.3  735.12   447.6  735.89     461  735.98
#Mann= 9 ,-1,0
       0      .1       0      20     .06       0     120     .08       0
     220     .06       0  287.52     .07       0   316.9    .045       0
   332.4     .07       0  362.52     .06       0  412.52     .08       0
Bank Sta=316.9,332.4
XS Rating Curve= 0 ,0
Exp/Cntr(USF)=0,0
Exp/Cntr=0.3,0.1

Type RM Length L Ch R = 1 ,428     ,123.1,119,114.8
XS GIS Cut Line= 6
1640238.87538145 382638.653844211640001.63787982382650.311013401
1639953.95031115382708.1977086371639890.36710499382785.380297065
1639850.82800633382821.1488260561639853.30238869382909.610872659
#Sta/Elev= 30
       0  778.53    18.8  773.28    98.9   771.4   118.9  767.85   138.9  761.47
   142.9  760.94     183  759.35     195  761.43   203.1  761.43   276.7  757.36
   287.1  753.82   302.8  751.22   307.8  748.75   318.1  740.94   328.5  734.35
   346.9  724.54  358.41 720.371   365.7  719.94  372.75720.3423   380.3  723.06
   385.5  723.68   401.1  721.91   433.3  720.67     459  720.03   481.2  721.16
   497.6  723.91   509.3  727.42   529.3  735.21   544.4  737.51   554.3  737.71
#Mann= 7 ,-1,0
       0     .05       0      50     .06       0  297.52      .1       0
  358.41    .045       0  372.75      .1       0  422.52     .06       0
  535.84     .07       0
Bank Sta=358.41,372.75
XS Rating Curve= 0 ,0
Exp/Cntr(USF)=0,0
Exp/Cntr=0.3,0.1

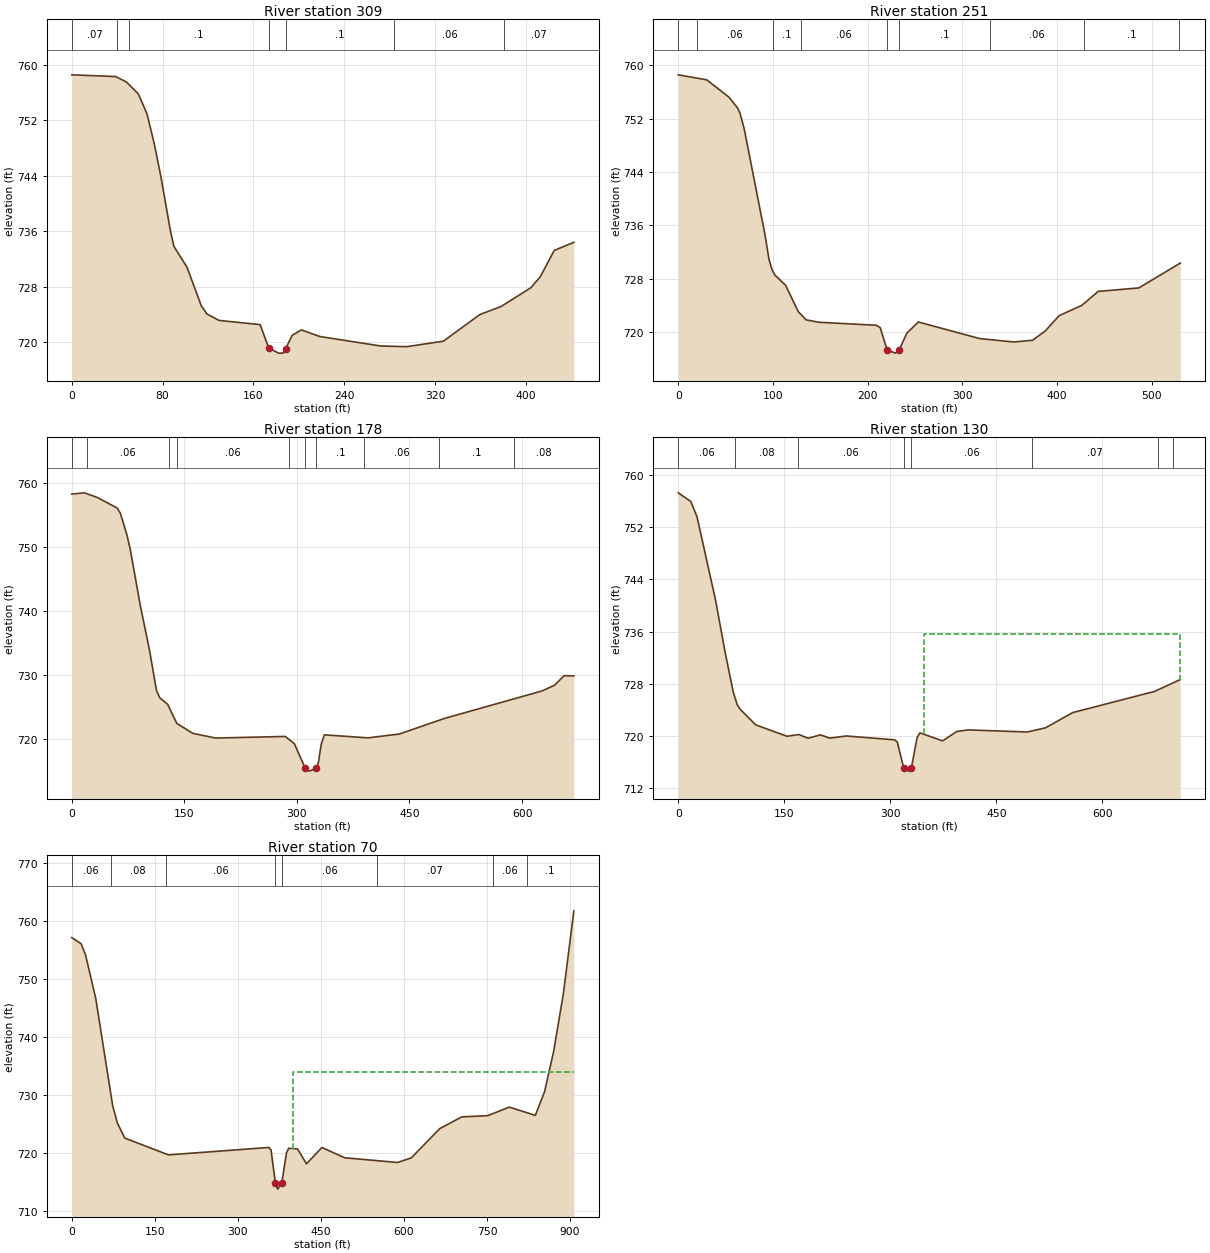
Type RM Length L Ch R = 1 ,309     ,58,58,58.1
XS GIS Cut Line= 4
1639929.05160011382573.7006538371639823.62206107382638.894981658
1639794.39288529382874.1155750361639810.95979443382953.567290203
#Sta/Elev= 30
       0  758.58    38.7  758.33    48.1  757.55    58.6  755.83    66.2  752.97
    72.5  748.74    78.3  744.05      87  735.98    89.9  733.85   101.5  730.82
     114  725.29     119  724.09   129.6  723.16   165.9  722.55  173.37719.2032
     182  718.44   186.1  718.44188.2141719.0425   194.1  721.01   202.2  721.79
   218.3  720.84     272  719.47   294.9  719.37   327.2  720.16   359.4  724.01
     378  725.16   404.3  727.88   412.5  729.44   424.8  733.25   442.1  734.42
#Mann= 7 ,-1,0
       0     .07       0      40     .06       0      50      .1       0
  173.37    .045       0188.2141      .1       0  283.96     .06       0
  380.99     .07       0
Bank Sta=173.37,188.2141
XS Rating Curve= 0 ,0
Exp/Cntr(USF)=0,0
Exp/Cntr=0.3,0.1

Type RM Length L Ch R = 1 ,251     ,71.7,72.3,69.6
XS GIS Cut Line= 4
1639907.48624028382553.0031955251639768.95667265382615.865352264
1639749.16673442382761.3796039741639764.69871056 382992.23856388
#Sta/Elev= 30
       0  758.59    30.1  757.84    53.6  755.24    62.6  753.63    65.2  752.87
    69.6  750.56    91.6  734.66    95.9   730.9    98.9  729.44   101.9  728.59
   113.5  727.01   126.7  723.09   135.1  721.84   148.7  721.48   209.3  721.03
   213.4  720.66  220.68717.3383   229.5  716.85   233.5  717.37   241.6  719.86
   253.7  721.52   318.2  719.04   354.3  718.52   374.3  718.78   387.4  720.13
   402.4  722.47   426.4  724.02   443.7  726.11   486.6  726.63   530.4  730.36
#Mann= 9 ,-1,0
       0     .07       0      20     .06       0     100      .1       0
     130     .06       0  220.68    .045       0   233.5      .1       0
  328.98     .06       0  428.98      .1       0  528.98     .08       0
Bank Sta=220.68,233.5
XS Rating Curve= 0 ,0
Exp/Cntr(USF)=0,0
Exp/Cntr=0.3,0.1

Type RM Length L Ch R = 1 ,178     ,47.8,47.9,47.7
XS GIS Cut Line= 4
1639907.48624028 382535.541485321639706.09451591 382624.01415036
1639715.40742802382993.038292697 1639739.9811211383069.086686354
#Sta/Elev= 30
       0  758.22    16.8  758.41    33.7   757.7    60.5  756.04    64.8  755.21
    73.6  751.81      78  749.56    91.3  740.85   103.5  733.92   112.9  727.57
   117.3  726.43   127.8  725.42   139.9  722.45   161.2   720.9   191.4  720.16
   284.5  720.41   296.6  719.28  311.04715.4752   316.5     715  325.58 715.455
   328.5  716.29   332.5  719.24   336.5  720.66   394.9  720.19   436.6  720.79
   496.6  723.22   626.4   727.5   643.3   728.4     656  729.89     669  729.86
#Mann= 10 ,-1,0
       0     .07       0      20     .06       0     130     .08       0
     140     .06       0  289.97      .1       0  311.04    .045       0
  325.58      .1       0  389.97     .06       0  489.97      .1       0
  589.11     .08       0
Bank Sta=311.04,325.58
XS Rating Curve= 0 ,0
Exp/Cntr(USF)=0,0
Exp/Cntr=0.3,0.1

Type RM Length L Ch R = 1 ,130     ,60,60.2,60.1
XS GIS Cut Line= 4
1639860.33962272 382526.228573211639658.94789836 382614.70123825
1639668.26081046382983.7253805881639709.64220857383097.456198162
#Sta/Elev= 30
       0  757.24    17.7  755.92    26.5   753.6    52.7  740.87    65.8  733.12
    77.8  726.74    83.3  724.84    87.6  724.11   109.5  721.73   153.7  719.98
   170.6  720.24   183.7  719.68   201.2  720.19   214.3  719.69   237.8  720.02
   305.8  719.43   309.8   719.1  318.79715.1774   325.8  714.64   329.8  715.17
   337.8  719.78   341.8   720.5   373.9  719.27   393.9   720.7   409.9  720.95
   493.9  720.63   519.5  721.27   557.9   723.6   673.9  726.85   710.1  728.66
#Mann= 8 ,-1,0
       0     .06       0      80     .08       0     170     .06       0
  318.79    .045       0   329.8     .06       0  499.97     .07       0
  679.11     .08       0  699.11      .1       0
#XS Ineff= 2 , 0
                          347.38          735.69
Permanent Ineff=
       F       F
Bank Sta=318.79,329.8
XS Rating Curve= 0 ,0
Exp/Cntr(USF)=0,0
Exp/Cntr=0.3,0.1

Type RM Length L Ch R = 1 ,70      ,,,
XS GIS Cut Line= 4
1639851.60876762382502.9462929361639601.32425468 382614.70123825
1639602.48836869382802.1235944531639720.06388407383231.681665502
#Sta/Elev= 30
       0  757.18      17  756.11      25  754.15    43.3  746.71    73.9   728.2
    82.4  725.23    95.8  722.63   174.7  719.74   355.9  721.02   359.9  720.61
   367.9  714.84   371.9  713.84  379.26714.8484   387.9   720.1   391.9  720.88
   407.9  720.76   423.9   718.2   451.9  721.01   493.1  719.24   588.4  718.43
   613.3  719.22   664.7  724.27   704.6  726.29   751.3   726.5   790.4  727.97
   837.3  726.55   853.9  730.59   870.4  737.55   888.1  747.59   906.9  761.79
#Mann= 8 ,-1,0
       0     .06       0      70     .08       0     170     .06       0
   367.9    .045       0  379.26     .06       0  551.53     .07       0
  761.53     .06       0  821.53      .1       0
#XS Ineff= 2 , 0
                          398.99             734
Permanent Ineff=
       F       F
Bank Sta=367.9,379.26
XS Rating Curve= 0 ,0
Exp/Cntr(USF)=0,0
Exp/Cntr=0.3,0.1
LCMann Table=0

Chan Stop Cuts=-1
Use User Specified Reach Order=0
Composite Channel Slope=5